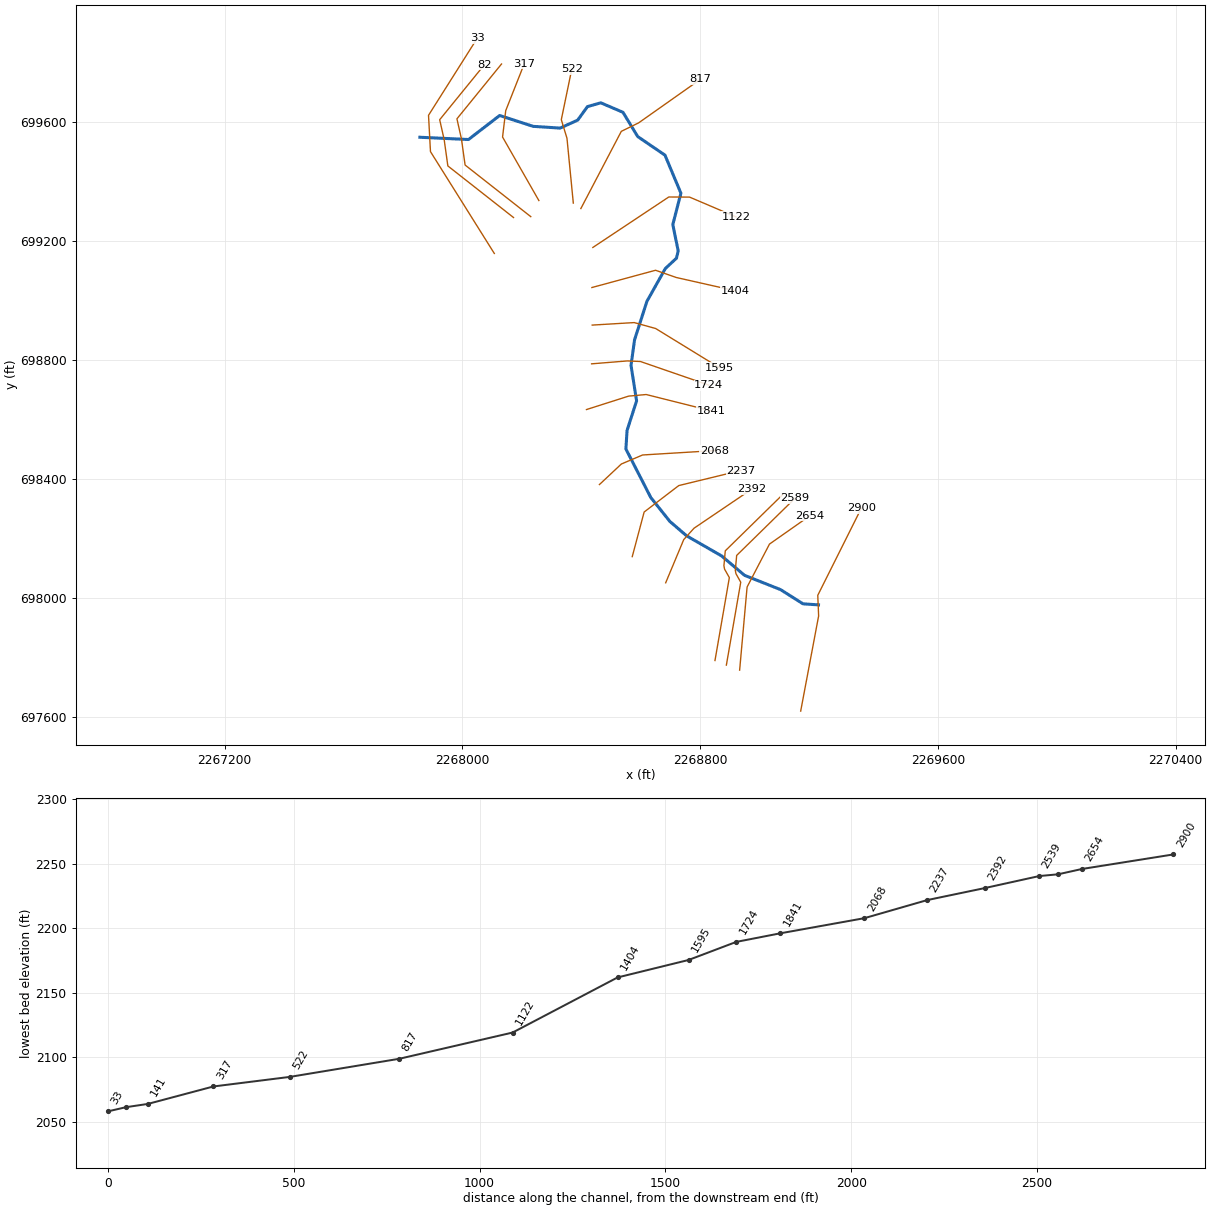
--- ROARCKT2.prj (project) ---

Proj Title=ROARCKT2
Current Plan=p01
Default Exp/Contr=0,0
English Units
Geom File=g01
Flow File=f01
Plan File=p01
BEGIN DESCRIPTION:
----------MODEL BY WOOD PLC 2022----------
AFH study
Randolph County, WV
HEC-RAS Version: RAS 6.2
Vertical Datum: NAVD88
Projection: NAD 1983 StatePlane West Virginia S FIPS 4702 (US Feet)
Terrain: 1-meter LIDAR (FEMA Region III 3DEP collected 2016-2018)
Land Use: 2019 NLCD
Hydrologic Method:
WV SIR2010-5033 regression equations
Additional Model Notes:
None
END DESCRIPTION:
DSS Export Rating Curves= 0
DSS Export Rating Curve Sorted= 0
DSS Export Volume Flow Curves= 0
DXF OffsetX= 0
DXF OffsetY= 0
DXF ScaleX= 0
DXF ScaleY= 0

--- ROARCKT2.p01 (plan) ---

Plan Title=Floodplain
Program Version=6.20
Short Identifier=Floodplain
Geom File=g01
Flow File=f01
Subcritical Flow
K Sum by GR= 0
Std Step Tol= 0.01
Critical Tol= 0.01
Num of Std Step Trials= 20
Max Error Tol= 0.3
Flow Tol Ratio= 0.001
Split Flow NTrial= 30
Split Flow Tol= 0.02
Split Flow Ratio= 0.02
Log Output Level= 0
Friction Slope Method= 1
Unsteady Friction Slope Method= 2
Unsteady Bridges Friction Slope Method= 1
Parabolic Critical Depth
Global Vel Dist= 0 , 0 , 0
Global Log Level= 0
CheckData=True
Encroach Param=-1 ,0,0, 0
Mapping Interval=1HOUR
Computation Time Step Use Courant=        0
Computation Time Step Use Time Series=    0
Computation Time Step Count To Double=0
Computation Time Step Max Doubling=0
Computation Time Step Max Halving=0
Computation Time Step Residence Courant=0
Run HTab= 0
Run UNet= 0
Run Sediment= 0
Run PostProcess= 0
Run WQNet= 0
Run RASMapper=-1
UNET Theta= 0
UNET Theta Warmup= 0
UNET ZTol= 0
UNET ZSATol= 0
UNET MxIter= 0
UNET Max Iter WO Improvement= 0
UNET MaxInSteps= 0
UNET DtIC= 0
UNET DtMin= 0
UNET MaxCRTS= 0
UNET WFStab= 0
UNET SFStab= 0
UNET WFX= 1
UNET SFX= 1
UNET Gravity=32.174
UNET 1D Methodology=Finite Difference
UNET DSS MLevel= 1
UNET Pardiso=0
UNET DZMax Abort= 0
UNET Use Existing IB Tables= 0
UNET Froude Reduction=False
UNET Froude Limit= 0
UNET Froude Power= 0
UNET D1 Cores= 0
UNET WindReference=Eulerian
UNET WindDragFormulation=Hsu (1988)
UNET D2 Coriolis=0
UNET D2 Cores= 0
UNET D2 Theta= 1
UNET D2 Theta Warmup= 1
UNET D2 Z Tol= 0.01
UNET D2 Volume Tol= 0.01
UNET D2 Max Iterations= 20
UNET D2 Equation= 0
UNET D2 RampUpFraction=0.1
UNET D2 TimeSlices= 1
UNET D2 Turbulence Formulation=Non-Conservative (original)
UNET D2 Eddy Viscosity=0.3
UNET D2 Transverse Eddy Viscosity=0.1
UNET D2 Smagorinsky Mixing=0
UNET D2 BCVolumeCheck=0
UNET D2 Cores=0
UNET D2 SolverType=PARDISO (Direct)
UNET D2 Minimum Iterations= 2147483647
UNET D2 Maximum Iterations= 2147483647
UNET D2 Restart Number= 10
UNET D2 Relaxation Coeff=1.3
UNET D2 SOR Precondition Iterations= 10
UNET D2 ILUT Maximum Fill= 8
UNET D2 ILUT Tolerance=1E-08
UNET D1D2 MaxIter= 0
UNET D1D2 ZTol=0.01
UNET D1D2 QTol=0.1
UNET D1D2 MinQTol=1
Write IC File= 0
Write IC File at Fixed DateTime=0
Write IC File at Sim End=0
Echo Input=False
Echo Parameters=False
Echo Output=False
Write Detailed= 0
HDF Write Warmup=0
HDF Write Time Slices=0
HDF Flush=0
HDF Compression= 1
HDF Chunk Size= 1
HDF Spatial Parts= 1
HDF Use Max Rows=0
HDF Fixed Rows= 1
Calibration Method= 0
Calibration Iterations= 20
Calibration Max Change=0.05
Calibration Tolerance=0.2
Calibration Maximum=1.5
Calibration Minimum=0.5
Calibration Optimization Method= 1
WQ AD Non Conservative
WQ ULTIMATE=-1
WQ Max Comp Step=1HOUR
WQ Output Interval=15MIN
WQ Output Selected Increments= 0
WQ Output face flow=0
WQ Output face velocity=0
WQ Output face area=0
WQ Output face dispersion=0
WQ Output cell volume=0
WQ Output cell surface area=0
WQ Output cell continuity=0
WQ Output cumulative cell continuity=0
WQ Output face conc=0
WQ Output face dconc_dx=0
WQ Output face courant=0
WQ Output face peclet=0
WQ Output face adv mass=0
WQ Output face disp mass=0
WQ Output cell mass=0
WQ Output cell source sink temp=0
WQ Output nsm pathways=0
WQ Output nsm derived pathways=0
WQ Create Restart=0
WQ Fixed Restart=0
WQ System Summary=0
WQ Write To DSS=0
Sorting and Armoring Iterations= 10
XS Update Threshold= 0.02
Bed Roughness Predictor= 0
Hydraulics Update Threshold= 0.02
Energy Slope Method= 1
Volume Change Method= 1
Sediment Retention Method= 0
Sediment TS Multiplier= 1
Warm Up Method= 0
XS Weighting Method= 0
Number of US Weighted Cross Sections= 1
Number of DS Weighted Cross Sections= 1
Upstream XS Weight=0
Main XS Weight=1
Downstream XS Weight=0
Number of DS XS's Weighted with US Boundary= 1
Upstream Boundary Weight= 1
Weight of XSs Associated with US Boundary= 0
Number of US XS's Weighted with DS Boundary= 1
Downstream Boundary Weight= 0.5
Weight of XSs Associated with DS Boundary= 0.5
Percentile Method= 0
Sediment Output Level= 3
Mass or Volume Output= 0
Output Increment Type= 1
Profile and TS Output Increment= 1
Transport Output Increment 1
XS Output Flag= 0
XS Output Increment= 10
Read HDF5 Sediment Hotstart= 0
Sediment Hotstart Type= 0
Write Gradation File= 0
Read Gradation Hotstart= 0
Write HDF5 File= 1
Write Binary Output= 1
Write DSS Sediment File= 0
DSS Sediment Output Type= 1
SV Curve= 0
Specific Gage Flag= 0
Subcell Erosion Methods= 0
Subcell Deposition Methods= 0
Advection Scheme= 1
Matrix Solver= 0
Implicit Weighting Factor= 1
Maximum Outer Loop Convergence Iterations= 5
Convergence Maximum Absolute= 0.001
Convergence RMSE= 0.0001
Grain Fractions Max Abs Error= 0.001
Max Subgrid Regions= 1
Max Subgrid Length Scale= 3.402823E+38
Initial Layer Thickness= 3.402823E+38
Min Layer Thickness= 3.402823E+38
Max Layer Thickness= 3.402823E+38
Number of Layers= 5

--- ROARCKT2.f01 (steady flow) ---

Flow Title=Flow
Program Version=6.20
Number of Profiles= 1
Profile Names=P100yr
River Rch & RM=ROARCKT2,Main,2900
     468
Boundary for River Rch & Prof#=ROARCKT2,Main            , 1
Up Type= 0
Dn Type= 3
Dn Slope=0.06728
DSS Import GetInterval= 0
DSS Import GetPeak= 0
DSS Import FillOption= 0

--- ROARCKT2.g01 (geometry) ---

Geom Title=Geometry
Program Version=6.20

River Reach=ROARCKT2        ,Main
Reach XY= 30
     2269198.271697977.6280000062269146.18700004697981.100000009
2269070.49299999698029.0170000052268949.36800002698077.095000014
2268872.03200004698142.4469999972268754.52000001698209.920000002
2268698.22000001698258.2639999992268634.03400002698338.738999993
2268550.30993445698501.9843403752268554.17299999698563.999000013
2268586.29099999 698663.826000022268567.54700002698782.935000002
2268579.34700005698868.6870000062268621.01400001698998.460999995
2268682.99300002699108.819999993     2268720.493699143.716000021
2268726.22200002 699168.282000022268708.16599999699256.823000014
2268735.38508905699362.1056409912268681.77800003 699490.15700002
     2268590.111699552.657000005     2268540.458699634.254000008
2268465.80500001699666.1980000142268421.01400003699653.351000011
     2268388.027699607.8649999952268329.00000004699581.128999993
2268238.23199999699587.0170000052268125.70600003699623.559000015
2268020.77299999699542.7559999972267857.21838759699550.330966444

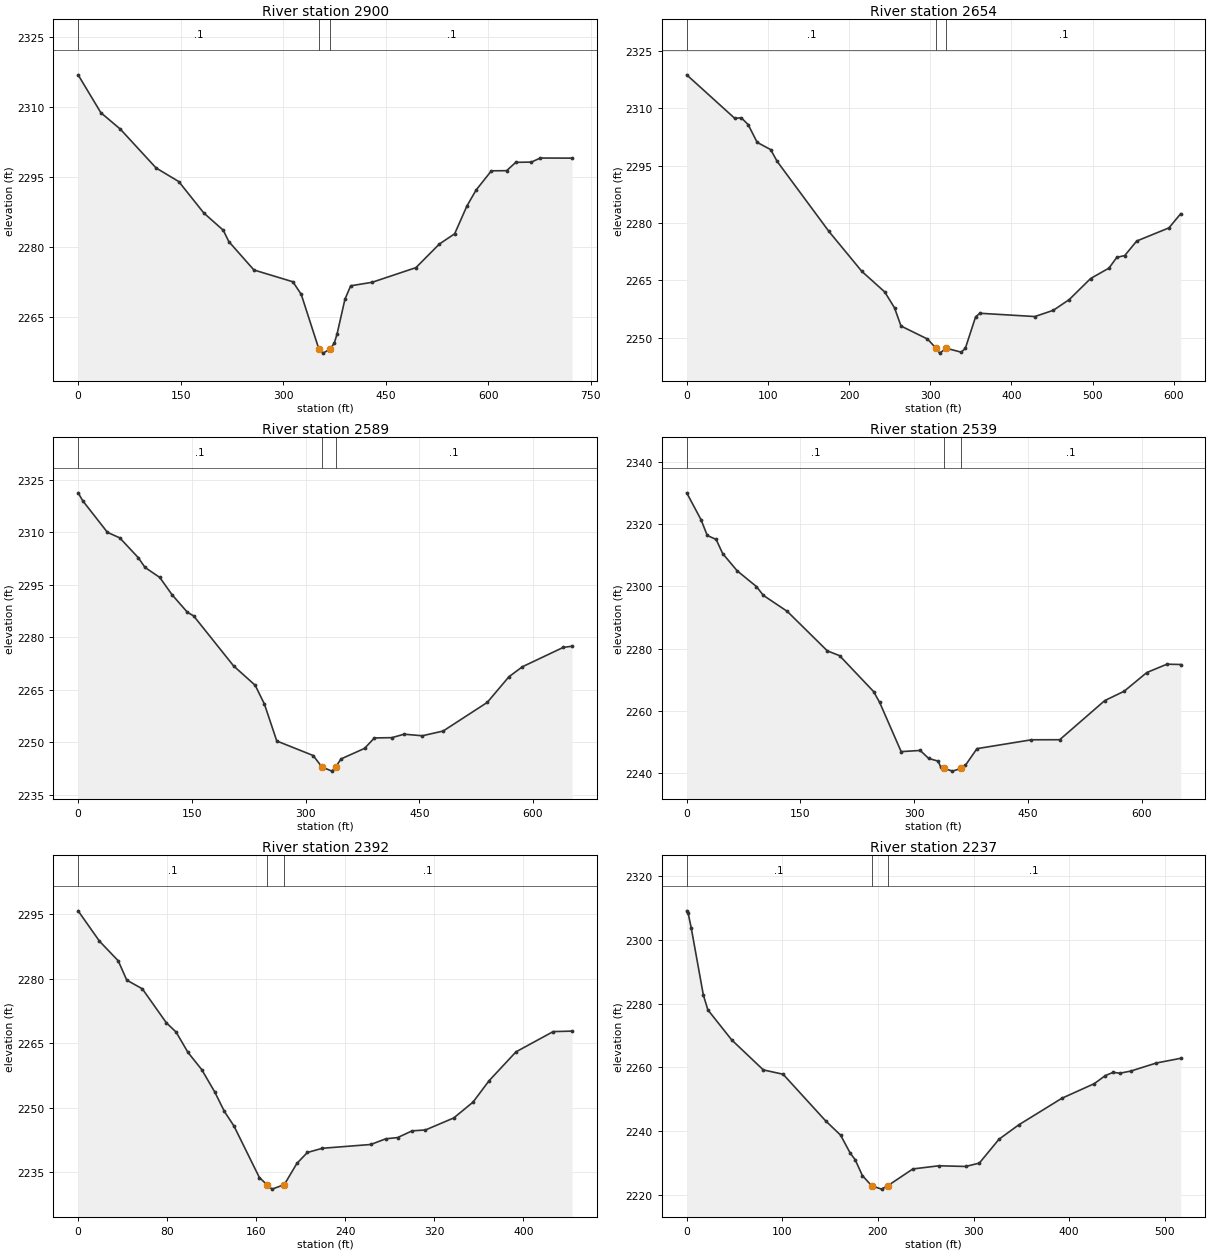
Type RM Length L Ch R = 1 ,2900    ,251,245.9,242.3
XS GIS Cut Line= 4
2269138.35728186697620.4524278442269198.72071158697940.474454514
2269195.83015585698009.8697593992269342.36603169698302.819004413
#Sta/Elev= 30
       0 2316.87    33.3 2308.75    61.8 2305.23     114 2296.92   147.3 2293.99
   183.9 2287.26   212.4 2283.56   220.5 2281.13   257.2 2275.05   314.2 2272.52
   326.4 2269.83  352.16 2258.14   358.4 2257.23  369.122258.142   374.9 2259.44
   378.8 2261.31   390.4 2268.81   398.8 2271.66   430.1 2272.41   494.2 2275.55
   528.5 2280.61   550.9 2282.81   568.8 2288.76   582.2 2292.17   604.6  2296.3
   626.9 2296.33   640.3 2298.12   663.2 2298.17   676.1 2299.04   722.7 2299.02
#Mann= 3 ,-1,0
       0      .1       0  352.16    .045       0  369.12      .1       0
Bank Sta=352.16,369.12
XS Rating Curve= 0 ,0
Exp/Cntr=0.3,0.1

Type RM Length L Ch R = 1 ,2654    ,57.6,64.6,67
XS GIS Cut Line= 4
2268932.96356549697758.2176201832268958.04963083 698037.74806259
2269033.30782686698181.9929383192269168.59339354698276.961614265
#Sta/Elev= 30
       0 2318.76    59.2 2307.37    67.2 2307.53    75.7 2305.73    86.8 2301.09
   103.4  2299.2   111.4 2296.12   175.2 2277.79   215.8 2267.33   243.9 2261.97
     256  2257.8     264 2253.04   296.6 2249.64   307.3 2247.21   311.6 2245.95
   319.8 2247.22   338.1 2246.21   343.2 2247.17   355.9 2255.44   361.2 2256.38
   428.9 2255.52   451.7 2257.16   471.3 2259.97   497.6 2265.47   520.2 2268.19
   529.9 2271.01   539.6 2271.47   554.4 2275.28   594.1 2278.72   608.6 2282.43
#Mann= 3 ,0,0
       0      .1       0   307.3    .045       0   319.8      .1       0
Bank Sta=307.3,319.8
XS Rating Curve= 0 ,0
Exp/Cntr(USF)=0,0
Exp/Cntr=0.3,0.1

Type RM Length L Ch R = 1 ,2589    ,51.7,50.6,52.2
XS GIS Cut Line= 6
2268888.32639669697775.0671304872268936.67435419698053.805794482
 2268920.5542442698082.4995943192268918.38552618 698093.82512175
2268922.96393089698143.9466048472269118.43557768698335.466140489
#Sta/Elev= 30
       0  2321.3     6.2    2319    38.7 2310.01    54.9 2308.44    79.3 2302.79
    88.2    2300   107.7 2297.13   123.9 2292.19   144.2 2287.17   152.4 2286.14
   205.1 2271.85   233.5 2266.34   245.7 2260.97     262 2250.42     310 2246.27
  321.582242.983   334.8 2241.81  339.542242.981   346.8  2245.3   377.8 2248.31
   390.7 2251.29   413.9 2251.37   429.9 2252.36   453.9 2251.91   481.4 2253.26
   539.6 2261.44   568.2 2268.77     586 2271.63   639.8 2277.15   651.5 2277.49
#Mann= 3 ,-1,0
       0      .1       0  321.58    .045       0  339.54      .1       0
Bank Sta=321.58,339.54
XS Rating Curve= 0 ,0
Exp/Cntr(USF)=0,0
Exp/Cntr=0.3,0.1

Type RM Length L Ch R = 1 ,2539    ,153.1,146.7,140.4
XS GIS Cut Line= 6
2268850.00765187697790.5117402372268898.35560937698069.250404231
2268882.23549938698097.9442040692268880.06678136698109.269731499
2268884.64518607698159.3912145962269080.11683286698350.910750239
#Sta/Elev= 30
       0 2330.21    18.9 2321.52    27.1 2316.46    38.8 2315.18    47.4 2310.63
    66.5 2305.07      92 2299.97   101.1 2297.13   132.6 2291.98   185.4 2279.25
   201.6 2277.69   246.4 2266.13   254.4 2262.64   282.8 2246.74   307.9 2247.12
   319.2 2244.53   331.4 2243.69   335.3 2241.66  339.912241.304   350.5 2240.45
  361.542241.304   367.5 2242.32   382.8  2247.7   454.7 2250.56   491.9 2250.58
   551.3  2263.2   576.8  2266.2   606.8 2272.25   633.3 2274.94   651.5 2274.84
#Mann= 3 ,-1,0
       0      .1       0  339.91    .045       0  361.54      .1       0
Bank Sta=339.91,361.54
XS Rating Curve= 0 ,0
Exp/Cntr(USF)=0,0
Exp/Cntr=0.3,0.1

Type RM Length L Ch R = 1 ,2392    ,155.7,154.6,152.7
XS GIS Cut Line= 4
2268684.20689906698051.9772308742268744.89271678698197.189723276
2268779.57032691698235.4795844572268973.90943365698366.965522851
#Sta/Elev= 30
       0 2295.83    19.2 2288.77      36 2284.22    43.7 2279.72    57.7 2277.69
    79.3 2269.78      88 2267.65    98.7  2262.9     111 2258.92   122.7 2253.72
   131.4 2249.18     140 2245.79   162.8 2233.82  169.562232.165   174.2 2231.12
  185.192232.167   196.5  2237.1   205.9 2239.64   219.4 2240.62   262.9  2241.5
   276.3 2242.82     287 2243.11     300 2244.67     312 2244.88   337.4 2247.67
   354.7 2251.35   369.1 2256.32   393.3 2263.04   426.7 2267.75   443.7 2267.86
#Mann= 3 ,-1,0
       0      .1       0  169.56    .045       0  185.19      .1       0
Bank Sta=169.56,185.19
XS Rating Curve= 0 ,0
Exp/Cntr(USF)=0,0
Exp/Cntr=0.3,0.1

Type RM Length L Ch R = 1 ,2237    ,171.1,168.8,166.9
XS GIS Cut Line= 4
2268571.68669057698139.8128640292268611.71208173698289.916601541
2268728.20477095698378.8570065982268936.83447127698429.563432392
#Sta/Elev= 30
       0  2309.1     1.5 2308.36     4.8  2303.6    17.4 2282.68    22.1 2278.05
      47 2268.63    80.1 2259.21   100.8 2257.85   145.3 2243.22   160.9 2238.76
     171  2233.1   176.1 2231.08   183.7 2226.07  193.482222.851   203.7 2221.82
  210.07 2222.85   236.5 2228.15   263.6 2229.14   291.8 2228.93     306 2229.98
   326.6 2237.48   347.2 2241.97   392.4 2250.33   426.3 2254.91   437.7 2257.42
     446 2258.45   452.8 2258.17   464.2 2258.83   491.2 2261.38   516.6 2262.85
#Mann= 3 ,-1,0
       0      .1       0  193.48    .045       0  210.07      .1       0
Bank Sta=193.48,210.07
XS Rating Curve= 0 ,0
Exp/Cntr=0.3,0.1

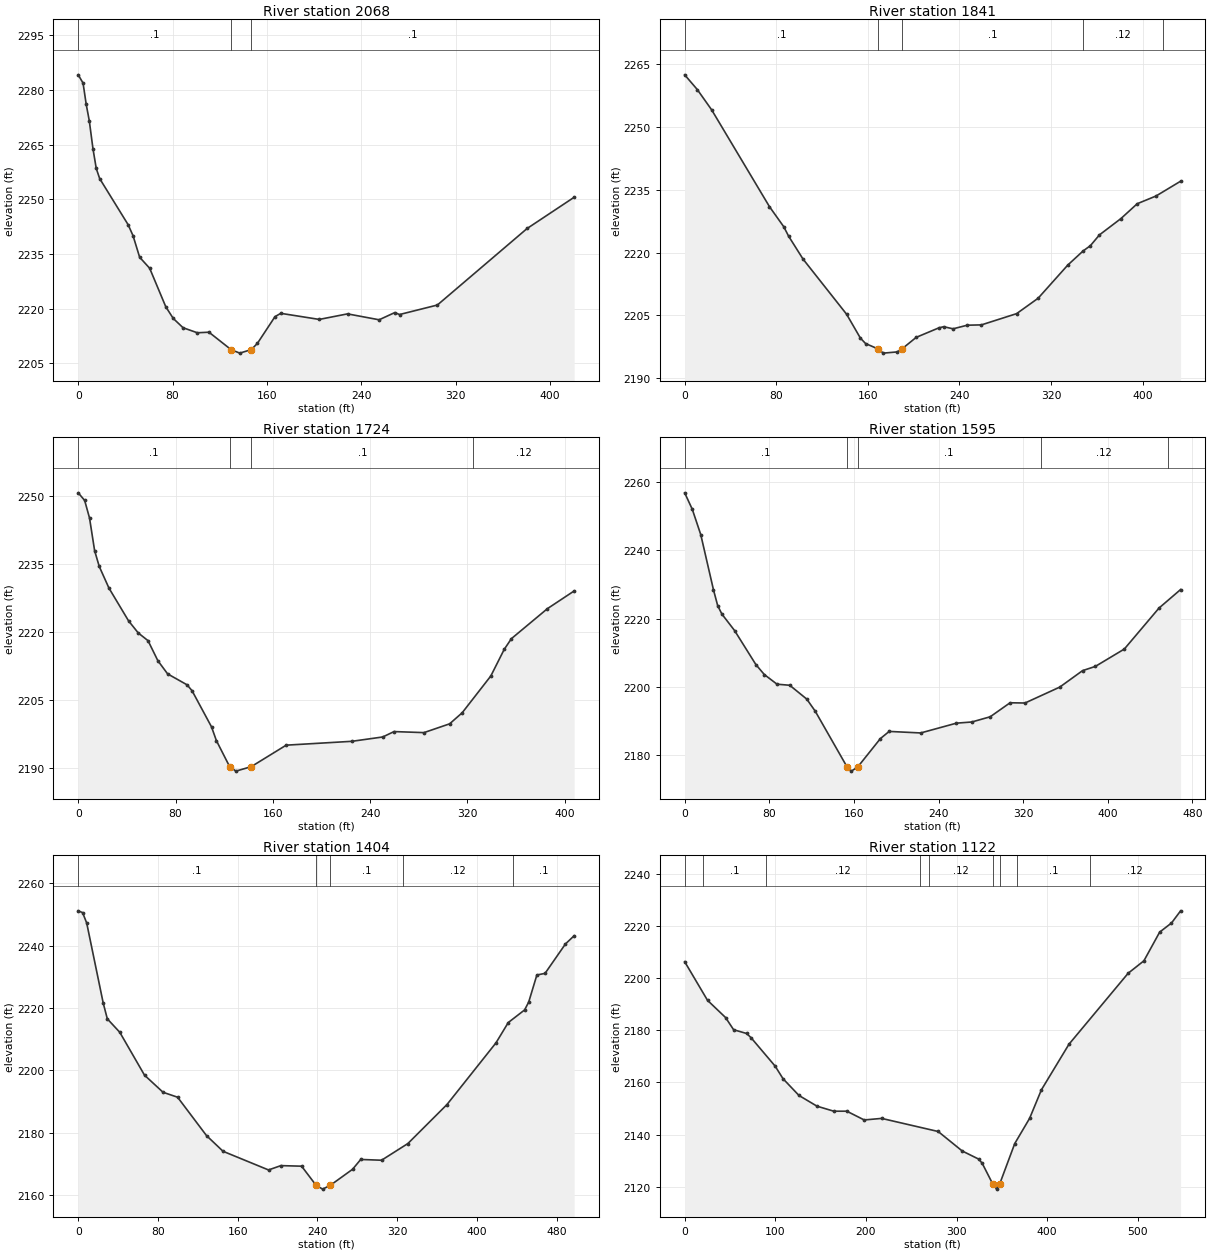
Type RM Length L Ch R = 1 ,2068    ,230.1,227.4,225.5
XS GIS Cut Line= 4
2268461.32966109698382.3498373762268535.01599158 698451.37711268
2268606.52987023698481.7796124452268847.98525802698496.435901544
#Sta/Elev= 30
       0 2284.17     4.1 2281.91     6.8 2276.04     9.4 2271.55    12.5 2263.92
    15.3 2258.47    18.2  2255.7    42.3 2243.06    46.5 2240.03    52.1 2234.11
    60.6 2231.09    74.3  2220.5    80.6 2217.32    88.9 2214.77     101 2213.39
   110.9 2213.54  129.622208.764     137  2207.8  146.782208.765     152 2210.49
   166.9 2217.81   171.8 2218.72   204.4 2217.05   228.4 2218.57   255.2 2216.95
   268.5 2218.93   272.5 2218.39   304.6    2221   380.7    2242   420.6 2250.57
#Mann= 3 ,-1,0
       0      .1       0  129.62    .045       0  146.78      .1       0
Bank Sta=129.62,146.78
XS Rating Curve= 0 ,0
Exp/Cntr(USF)=0,0
Exp/Cntr=0.3,0.1

Type RM Length L Ch R = 1 ,1841    ,118.8,117.5,116.7
XS GIS Cut Line= 4
2268417.70105137698634.5464397912268559.53727732 698679.73678806
2268618.43439831698685.0940908912268837.02920476 698630.34471133
#Sta/Elev= 30
       0 2262.47      11 2258.96    23.6 2254.09    74.1 2230.97    86.6 2226.17
    90.8 2223.93   103.4 2218.46   141.5 2205.27   153.5 2199.59   158.1 2198.27
   168.82197.018   173.6 2195.99   185.7 2196.28  189.952197.019   202.3 2199.76
   222.2 2202.04   226.3  2202.3   234.5  2201.8   246.9 2202.66   259.3 2202.74
     290 2205.42   308.8  2209.1   334.7 2217.02     348 2220.37   354.5 2221.67
   362.4 2224.24   381.1 2228.12   395.4 2231.68   411.8 2233.52   433.3 2237.06
#Mann= 5 ,-1,0
       0      .1       0   168.8    .045       0  189.95      .1       0
     348     .12       0     418      .1       0
Bank Sta=168.8,189.95
XS Rating Curve= 0 ,0
Exp/Cntr=0.3,0.1

Type RM Length L Ch R = 1 ,1724    ,130.2,128.3,126.5
XS GIS Cut Line= 4
2268434.91838628698788.317608607 2268555.2063464698798.070686455
2268599.42029932698796.1200708852268828.94273134698716.795037722
#Sta/Elev= 30
       0 2250.81     5.3 2249.13     9.3 2245.25    13.5 2238.03    17.3 2234.55
    25.3 2229.77    41.4 2222.55    49.4 2219.87    57.4 2218.18    65.5 2213.75
    73.5 2210.85    89.5 2208.43    93.6 2207.13   109.6 2199.16   113.6 2196.13
  124.522190.371   129.7 2189.38  142.292190.369     171 2195.11     225 2195.96
   250.4 2196.92   259.7 2198.11   284.3 2197.88   305.4 2199.82   315.7 2202.25
   339.3 2210.39   350.3 2216.26   356.2 2218.62   385.8 2225.24   407.8 2229.15
#Mann= 4 ,-1,0
       0      .1       0  124.52    .045       0  142.29      .1       0
  324.94     .12       0
Bank Sta=124.52,142.29
XS Rating Curve= 0 ,0
Exp/Cntr(USF)=0,0
Exp/Cntr=0.3,0.1

Type RM Length L Ch R = 1 ,1595    ,190.6,190.9,190.4
XS GIS Cut Line= 4
2268437.02059758698918.612973283 2268578.3103934698927.059645859
2268650.49104996698907.0947834062268865.49726099698775.019539488
#Sta/Elev= 30
       0 2256.87     7.2 2252.04    15.2 2244.63    27.2 2228.49    31.2 2223.83
    35.2 2221.35    47.2 2216.52    67.3 2206.57    75.3 2203.64    87.3 2200.82
    99.3 2200.51   115.4 2196.46   123.4 2192.92  153.412176.636   157.6 2175.36
  163.742176.638     185 2184.89   193.3 2186.99   223.1 2186.54   256.9 2189.41
   271.4 2189.75   288.8 2191.28   307.6 2195.38   321.7 2195.31   354.5 2199.96
   376.1 2204.79   388.2 2206.03   415.6 2211.12   448.4 2223.13   468.8 2228.55
#Mann= 5 ,-1,0
       0      .1       0  153.41    .045       0  163.74      .1       0
  336.43     .12       0  456.43      .1       0
Bank Sta=153.41,163.74
XS Rating Curve= 0 ,0
Exp/Cntr(USF)=0,0
Exp/Cntr=0.3,0.1

Type RM Length L Ch R = 1 ,1404    ,278.7,282.3,283.1
XS GIS Cut Line= 4
 2268435.9720886699044.9386270012268650.06890508 699102.99610648
2268719.86962071699078.6707531442268916.72411831699034.319848357
#Sta/Elev= 30
       0 2251.21     4.4 2250.63     8.5 2247.31    25.1 2221.56    29.2 2216.51
    41.7  2212.2    66.5 2198.43    85.1 2192.93    99.7 2191.34   128.7 2179.01
   145.3 2173.97   190.9 2167.98   203.3 2169.37   224.1 2169.19   238.62163.059
   245.2 2161.82  252.962163.058   275.2 2168.19   283.4 2171.35   304.3  2171.1
   330.7 2176.46   369.9 2188.98   419.1 2208.81   431.4 2215.32   447.8 2219.38
   451.9  2221.9   460.1  2230.6   468.3 2231.12   488.8 2240.58   497.5 2243.21
#Mann= 5 ,-1,0
       0      .1       0   238.6    .045       0  252.96      .1       0
  325.75     .12       0  435.75      .1       0
Bank Sta=238.6,252.96
XS Rating Curve= 0 ,0
Exp/Cntr=0.3,0.1

Type RM Length L Ch R = 1 ,1122    ,302.9,305.1,304.1
XS GIS Cut Line= 4
2268439.17775627699179.7115183292268694.61834633699349.439338711
2268764.65859794699349.0455748772268921.44239211699282.128883081
#Sta/Elev= 30
       0 2206.23    25.2 2191.43    45.1 2184.84      54 2180.16    68.4 2178.72
    73.2 2177.12    99.9 2166.18   108.5  2161.4   126.1 2154.98     146 2150.87
   164.5 2148.95   178.9 2148.95   198.1 2145.59   217.3 2146.19   279.7 2141.17
   306.2 2133.71   324.4 2130.59   328.2 2129.04  339.862121.093   344.2 2119.09
   347.6 2121.09   364.2 2136.56   380.6 2146.22   393.6 2157.14     424  2174.6
   489.3  2201.8   506.7 2206.57   524.1 2217.57   537.1 2221.04   547.2 2225.72
#Mann= 9 ,-1,0
       0     .12       0      20      .1       0      90     .12       0
     260      .1       0     270     .12       0  339.86    .045       0
   347.6     .12       0  366.69      .1       0  446.73     .12       0
Bank Sta=339.86,347.6
XS Rating Curve= 0 ,0
Exp/Cntr(USF)=0,0
Exp/Cntr=0.3,0.1

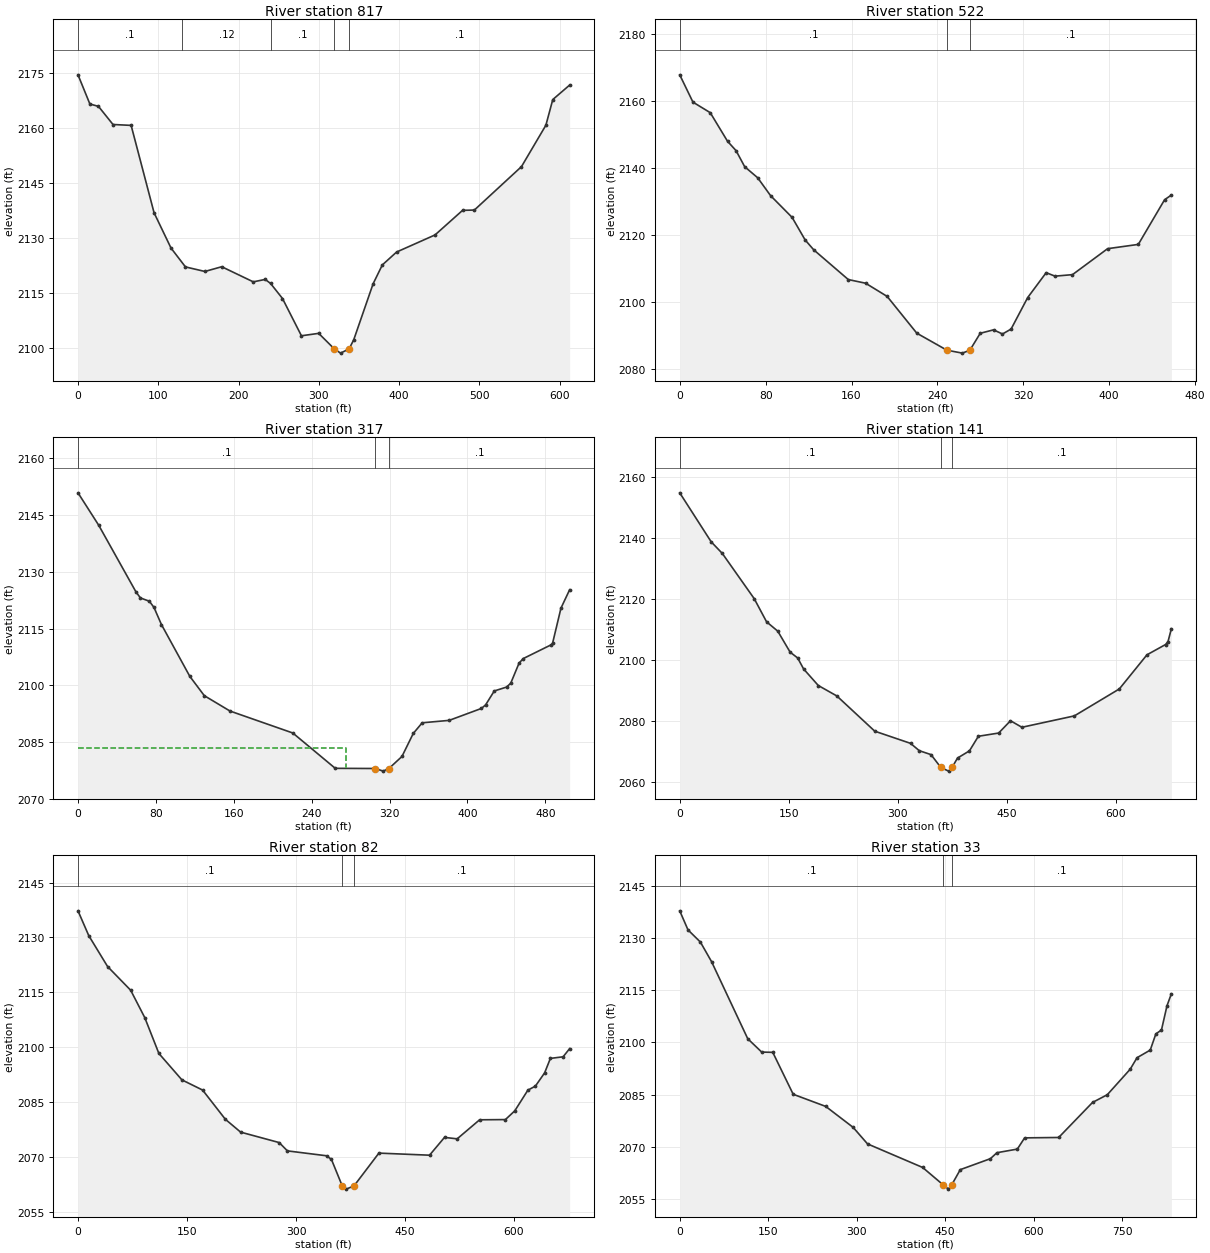
Type RM Length L Ch R = 1 ,817     ,283.2,295,309.4
XS GIS Cut Line= 4
2268398.80238733699310.5530240412268534.89228932699570.257970694
2268593.07186286699598.652257663   2268801.20558699745.382863041
#Sta/Elev= 30
       0 2174.59    14.8 2166.64    25.5 2165.99    43.6 2161.05    66.2 2160.81
    94.8 2136.98   115.9 2127.37   133.9 2122.23   158.1 2120.99   179.1 2122.28
   218.4 2118.16   233.3 2118.82     240 2117.71   254.8 2113.62   278.4 2103.46
   299.9 2104.12  319.352099.889   327.2 2098.73   337.82099.888   343.6 2102.38
   367.7 2117.62   379.2 2122.77     397 2126.29   444.9 2130.95   479.2 2137.65
   493.9 2137.73   552.6 2149.57     583 2160.85   591.6 2167.85   612.6  2171.8
#Mann= 5 ,-1,0
       0      .1       0     130     .12       0     240      .1       0
  319.35    .045       0   337.8      .1       0
Bank Sta=319.35,337.8
XS Rating Curve= 0 ,0
Exp/Cntr=0.3,0.1

Type RM Length L Ch R = 1 ,522     ,208.4,204.7,199
XS GIS Cut Line= 4
2268373.39072112 699328.934465732268352.07303446699547.002921301
 2268333.0154366699609.4853391532268368.21464566699779.300429901
#Sta/Elev= 30
       0 2167.85    12.3 2159.69    28.4 2156.54    44.5    2148    52.5 2145.17
    60.5 2140.38    72.6 2137.08    84.6 2131.74   104.7 2125.22   116.8 2118.49
   124.8 2115.54     157 2106.65   173.1 2105.56   193.2 2101.61   220.8 2090.62
  248.822085.539   263.2 2084.66  270.252085.538   279.9  2090.6   292.3 2091.62
   300.6 2090.38   308.6 2091.85   324.1 2101.28   341.3 2108.71   349.5 2107.67
   365.8 2108.12   398.5 2115.88   427.1 2117.16   451.6 2130.52   457.9 2131.91
#Mann= 3 ,-1,0
       0      .1       0  248.82    .045       0  270.25      .1       0
Bank Sta=248.82,270.25
XS Rating Curve= 0 ,0
Exp/Cntr(USF)=0,0
Exp/Cntr=0.3,0.1

Type RM Length L Ch R = 1 ,317     ,170.1,176.6,173.9
XS GIS Cut Line= 4
2268257.50116639699337.5083589732268135.38717156699551.067313752
2268146.02725038699639.7679110642268208.35688958699797.468074717
#Sta/Elev= 30
       0 2150.91    21.3 2142.32    59.5 2124.71    64.1  2123.1    73.3 2122.22
      78  2120.6    85.7 2116.05   114.8 2102.36   129.7 2097.24   156.1 2093.17
   220.6 2087.36   264.2 2078.01  305.322077.963   313.4 2077.27  319.292077.958
   332.7 2081.15   344.3 2087.24   353.5 2090.06   381.2  2090.7   414.3 2093.86
   418.6  2094.8   427.5 2098.48   440.1 2099.51   444.4 2100.53     453 2105.87
   457.3 2107.06   486.1 2110.72   487.4 2111.13     496  2120.4   504.9 2125.27
#Mann= 3 ,-1,0
       0      .1       0  305.32    .045       0  319.29      .1       0
#XS Ineff= 2 , 0
          274.81  2083.4
Permanent Ineff=
       F       F
Bank Sta=305.32,319.29
XS Rating Curve= 0 ,0
Exp/Cntr(USF)=0,0
Exp/Cntr=0.3,0.1

Type RM Length L Ch R = 1 ,141     ,58.6,59,59.2
XS GIS Cut Line= 5
2268230.22853963699283.3784231252268009.34473376 699456.86227065
2267997.02074459699545.0261931632267981.85275793699612.334134005
2268131.87070015699796.714120102
#Sta/Elev= 30
       0 2154.86    43.3 2138.81    58.6 2135.01   102.5  2120.2   119.5 2112.62
   134.9 2109.56   151.9 2102.69   162.3 2100.78   170.5 2097.17   190.7 2091.76
   216.2 2088.34   268.4  2076.8   317.6 2072.82   329.7 2070.41   345.8 2069.13
  359.342064.921     370 2063.72  374.73 2064.92   382.3    2068   398.7 2070.36
     411 2075.14   438.9 2076.19   455.2 2080.22   470.9 2078.08   543.1 2081.81
     605 2090.64     643 2101.81   668.6 2105.18     672 2106.17   676.6 2110.36
#Mann= 3 ,-1,0
       0      .1       0  359.34    .045       0  374.73      .1       0
Bank Sta=359.34,374.73
XS Rating Curve= 0 ,0
Exp/Cntr(USF)=0,0
Exp/Cntr=0.3,0.1

Type RM Length L Ch R = 1 ,82      ,49.9,48.6,47.6
XS GIS Cut Line= 5
2268172.21756382699280.4035012892267951.33375796699453.887348814
2267939.00976879699542.0512713262267923.84178212699609.359212169
2268073.85972434699793.739198266
#Sta/Elev= 30
       0 2137.29    14.8 2130.51    40.7 2122.06    72.5 2115.57    91.9 2108.08
   111.3 2098.29     143 2091.06   171.5 2088.27   202.8 2080.28   223.8 2076.77
   276.9 2073.91   288.2 2071.64   342.1  2070.3   348.8  2069.3  363.642062.068
     369 2061.18  379.882062.068   414.1 2071.03   483.8 2070.46   504.4 2075.33
   521.8 2074.93   552.7 2080.14   588.2  2080.2   601.1 2082.59   619.1 2088.24
   629.5 2089.36   642.2 2092.98   650.1 2096.93   667.6 2097.37   676.6 2099.61
#Mann= 3 ,-1,0
       0      .1       0  363.64    .045       0  379.88      .1       0
Bank Sta=363.64,379.88
XS Rating Curve= 0 ,0
Exp/Cntr(USF)=0,0
Exp/Cntr=0.3,0.1

Type RM Length L Ch R = 1 ,33      ,,,
XS GIS Cut Line= 4
2268107.61043158699159.5350219892267892.86785911699501.982751809
2267886.31272928699624.2095167832268050.24867952699883.397666438
#Sta/Elev= 30
       0 2137.78      14 2132.31      35 2128.82    53.9 2123.21   115.3 2101.07
   138.9 2097.25   157.7 2097.17   192.3 2085.14   247.5 2081.65   293.9 2075.64
   318.3  2070.9   411.7 2064.14   445.9 2059.23   455.5 2057.92  461.292059.231
   475.5 2063.51   526.6 2066.66   537.6 2068.37   572.2 2069.41   584.6 2072.63
   642.3 2072.74   699.7  2082.8   724.7 2085.01   763.5 2092.33   775.1 2095.63
   797.5 2097.82     807 2102.47   816.5 2103.58   825.9 2110.56   833.3 2113.97
#Mann= 3 ,-1,0
       0      .1       0   445.9    .045       0  461.29      .1       0
Bank Sta=445.9,461.29
XS Rating Curve= 0 ,0
Exp/Cntr(USF)=0,0
Exp/Cntr=0.3,0.1
LCMann Table=0

Chan Stop Cuts=-1
Use User Specified Reach Order=0
Composite Channel Slope=5